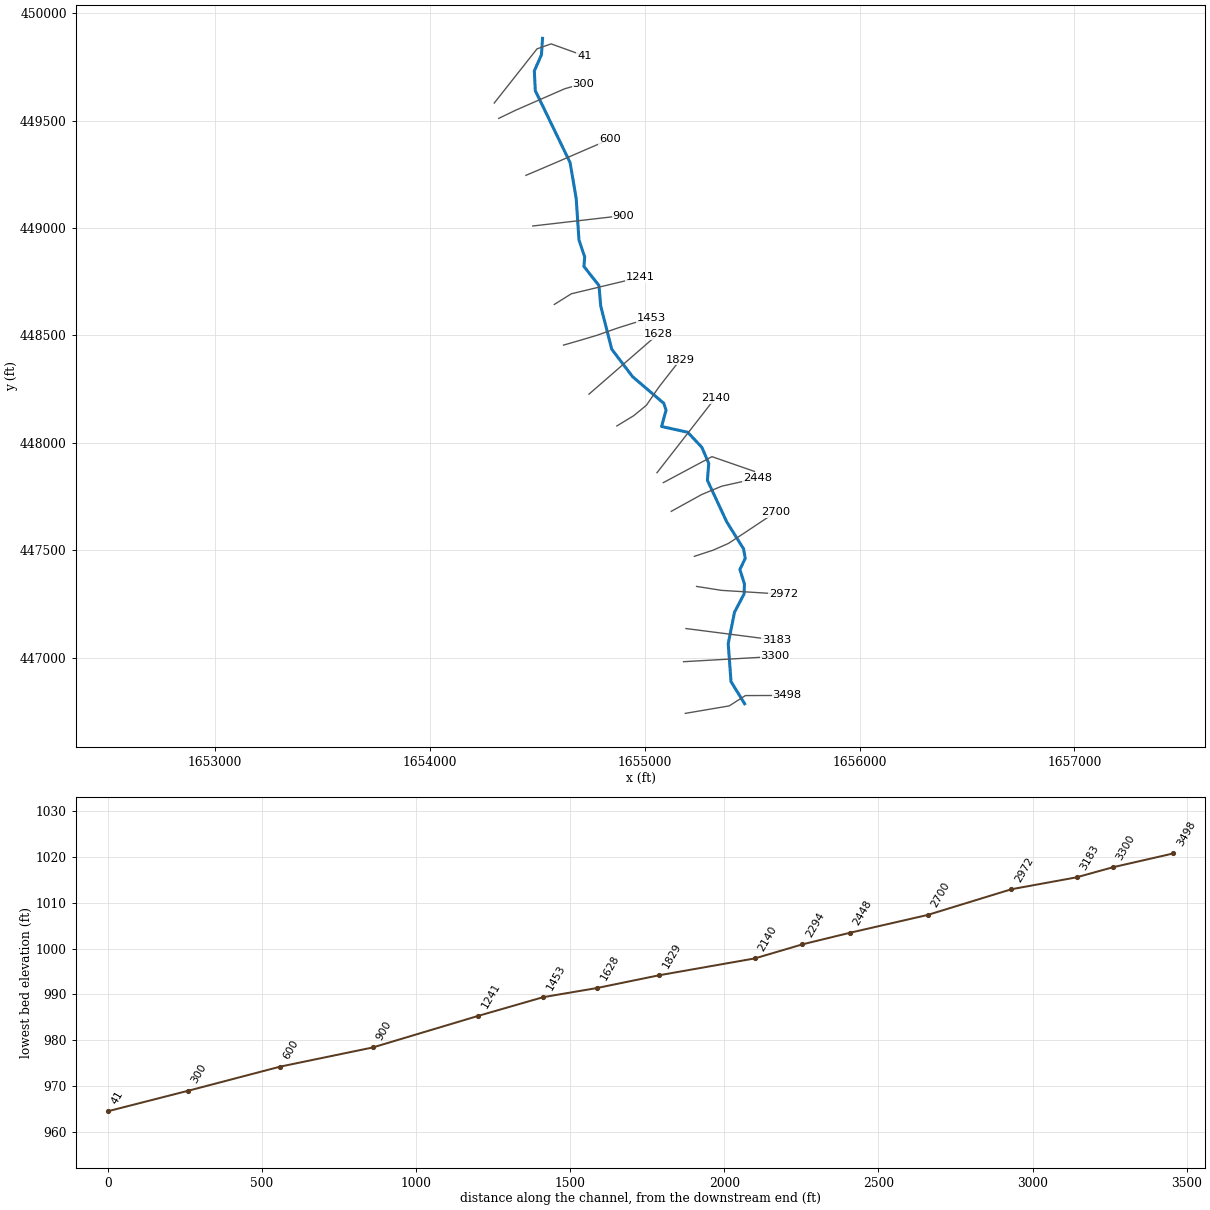
--- LtleLaurlRn.prj (project) ---

Proj Title=LtleLaurlRn
Current Plan=p01
Default Exp/Contr=0,0
English Units
Geom File=g01
Flow File=f01
Plan File=p01
BEGIN DESCRIPTION:
---------- MODELED AS PART OF WVEM CTP PROGRAM, 2025----------
Stream Name: Little Laurel Run
Flood Zone: AFH
Marshall County, WV
HEC-RAS Version: RAS 6.6
Vertical Datum: NAVD88
Projection: NAD 1983 StatePlane West Virginia N FIPS 4701 (US Feet)
Terrain: 1-meter West Virginia FEMA R3 South Central (collected 2018-2019)
Land Use: 2024 NLCD
Hydrologic Method:
Duda et al., "Estimation of magnitude and frequency of floods for rural, unregulated streams in and near Virginia and West Virginia." September 8, 2025.
Additional Model Notes:
None
END DESCRIPTION:
DSS Export Rating Curves= 0
DSS Export Rating Curve Sorted= 0
DSS Export Volume Flow Curves= 0
DXF OffsetX= 0
DXF OffsetY= 0
DXF ScaleX= 0
DXF ScaleY= 0

--- LtleLaurlRn.p01 (plan) ---

Plan Title=Floodplain
Program Version=6.60
Short Identifier=Floodplain
Geom File=g01
Flow File=f01
Subcritical Flow
K Sum by GR= 0
Std Step Tol= 0.01
Critical Tol= 0.01
Num of Std Step Trials= 20
Max Error Tol= 0.3
Flow Tol Ratio= 0.001
Split Flow NTrial= 30
Split Flow Tol= 0.02
Split Flow Ratio= 0.02
Log Output Level= 0
Friction Slope Method= 1
Unsteady Friction Slope Method= 2
Unsteady Bridges Friction Slope Method= 1
Parabolic Critical Depth
Global Vel Dist= 0 , 0 , 0
Global Log Level= 0
CheckData=False
Encroach Param=-1 ,0,0, 0
Flow Ratio Tolerance=0.1
Flow Ratio Min Ratio=0.5
Flow Ratio Max Ratio=4
Flow Ratio Max Iterations= 10
Mapping Interval=1HOUR
Computation Time Step Use Courant=        0
Computation Time Step Use Time Series=    0
Computation Time Step Count To Double=0
Computation Time Step Max Doubling=0
Computation Time Step Max Halving=0
Computation Time Step Residence Courant=0
Run HTab= 0
Run UNet= 0
Run Sediment= 0
Run PostProcess= 0
Run WQNet= 0
Run RASMapper=-1
UNET Theta= 0
UNET Theta Warmup= 0
UNET ZTol= 0
UNET ZSATol= 0
UNET MxIter= 0
UNET Max Iter WO Improvement= 0
UNET MaxInSteps= 0
UNET DtIC= 0
UNET DtMin= 0
UNET MaxCRTS= 0
UNET WFStab= 0
UNET SFStab= 0
UNET WFX= 1
UNET SFX= 1
UNET Gravity=32.17405
UNET 1D Methodology=Finite Difference
UNET DSS MLevel= 1
UNET Pardiso=0
UNET DZMax Abort= 0
UNET Use Existing IB Tables= 0
UNET Froude Reduction=False
UNET Froude Limit= 0
UNET Froude Power= 0
UNET D1 Cores= 0
UNET WindReference=Eulerian
UNET WindDragFormulation=Hsu (1988)
UNET D2 Coriolis=0
UNET D2 Cores= 0
UNET D2 Theta= 1
UNET D2 Theta Warmup= 1
UNET D2 Z Tol= 0.01
UNET D2 Volume Tol= 0.01
UNET D2 Max Iterations= 20
UNET D2 Advanced Convergence=0
UNET D2 WS Max Tol=0.15
UNET D2 WS RMS Tol=0.002
UNET D2 WS Stall Tol=1
UNET D2 Equation= 0
UNET D2 RampUpFraction=0.1
UNET D2 TimeSlices= 1
UNET D2 Turbulence Formulation=Non-Conservative (original)
UNET D2 Eddy Viscosity=0.3
UNET D2 Transverse Eddy Viscosity=0.1
UNET D2 Smagorinsky Mixing=0
UNET D2 BCVolumeCheck=0
UNET D2 Cores=0
UNET D2 SolverType=PARDISO (Direct)
UNET D2 Minimum Iterations= 3
UNET D2 Maximum Iterations= 30
UNET D2 Restart Number= 10
UNET D2 Relaxation Coeff=1.3
UNET D2 SOR Precondition Iterations= 10
UNET D2 ILUT Maximum Fill= 8
UNET D2 ILUT Tolerance=1E-08
UNET D2 Convergence Tolerance=0.00001
PS Theta= 1
PS WS Tol= 0.01
PS Volume Tol= 0.01
PS Max Iterations= 20
PS Equation= 0
PS Advance Time Step=-1
PS Target Courant=0.9
PS Time Slices= 1
PS Iterate With 2D=0
PS Project Initial WSE from DS=-1
PS Ramp Up Initial WSE from US=-1
PS Cores=0
UNET D1D2 MaxIter= 0
UNET D1D2 ZTol=0.01
UNET D1D2 QTol=0.1
UNET D1D2 MinQTol=1
Write IC File= 0
Write IC File at Fixed DateTime=0
Write IC File at Sim End=0
Echo Input=False
Echo Parameters=False
Echo Output=False
Write Detailed= 0
HDF Write Warmup=0
HDF Write Time Slices=0
HDF Flush=0
HDF Compression= 1
HDF Chunk Size= 1
HDF Spatial Parts= 1
HDF Use Max Rows=0
HDF Fixed Rows= 1
Calibration Method= 0
Calibration Iterations= 20
Calibration Max Change=0.05
Calibration Tolerance=0.2
Calibration Maximum=1.5
Calibration Minimum=0.5
Calibration Optimization Method= 1
WQ AD Non Conservative
WQ ULTIMATE=-1
WQ Max Comp Step=1HOUR
WQ Output Interval=15MIN
WQ Output Selected Increments= 0
WQ Create Restart=0
WQ Fixed Restart=0
WQ System Summary=0
WQ Write To DSS=0
Sorting and Armoring Iterations= 10
XS Update Threshold= 0.02
Bed Roughness Predictor= 0
Processes Affected by Predictor=Sediment Only
Hydraulics Update Threshold= 0.02
Energy Slope Method= 1
Volume Change Method= 1
Sediment Retention Method= 0
Sediment TS Multiplier= 1
Warm Up Method= 0
XS Weighting Method= 0
Number of US Weighted Cross Sections= 1
Number of DS Weighted Cross Sections= 1
Upstream XS Weight=0
Main XS Weight=1
Downstream XS Weight=0
Number of DS XS's Weighted with US Boundary= 1
Upstream Boundary Weight= 1
Weight of XSs Associated with US Boundary= 0
Number of US XS's Weighted with DS Boundary= 1
Downstream Boundary Weight= 0.5
Weight of XSs Associated with DS Boundary= 0.5
Percentile Method= 0
Sediment Output Level= 3
Mass or Volume Output= 0
Output Increment Type= 1
Profile and TS Output Increment= 1
Transport Output Increment 1
XS Output Flag= 0
XS Output Increment= 10
Read HDF5 Sediment Hotstart= 0
Sediment Hotstart Type= 0
Write Gradation File= 0
Read Gradation Hotstart= 0
Write HDF5 File= 1
Write Binary Output= 1
Write DSS Sediment File= 0
DSS Sediment Output Type= 1
SV Curve= 0
Specific Gage Flag= 0
Subcell Erosion Methods= 0
Subcell Deposition Methods= 0
Advection Scheme= 1
Matrix Solver= 0
Implicit Weighting Factor= 1
Maximum Outer Loop Convergence Iterations= 5
Convergence Maximum Absolute= 0.001
Convergence RMSE= 0.0001
Grain Fractions Max Abs Error= 0.001
Max Subgrid Regions= 1
Max Subgrid Length Scale= 3.402823E+38
Initial Layer Thickness= 3
Min Layer Thickness= 0.1
Max Layer Thickness= 6
Number of Layers= 5

--- LtleLaurlRn.f01 (steady flow) ---

Flow Title=Flow
Program Version=6.60
Number of Profiles= 1
Profile Names=P100yr
River Rch & RM=LtleLaurlRn,Main,3498
     844
Boundary for River Rch & Prof#=LtleLaurlRn,Main            , 1
Up Type= 0
Dn Type= 3
Dn Slope=0.009775
DSS Import GetInterval= 0
DSS Import GetPeak= 0
DSS Import FillOption= 0

--- LtleLaurlRn.g01 (geometry) ---

Geom Title=Geometry
Program Version=6.60

River Reach=LtleLaurlRn     ,Main
Reach XY= 30
     1655465.087      446786.371     1655401.876      446889.087
     1655388.792      447065.758     1655418.121      447212.405
     1655462.584      447297.149     1655464.241      447343.131
     1655443.114      447411.068     1655467.969      447462.849
     1655460.098      447507.175     1655382.633      447631.036
     1655291.912      447825.735     1655298.126      447905.271
     1655265.814      447979.836     1655200.362      448049.431
     1655078.572      448076.357     1655099.544      448152.321
     1655089.187      448184.037     1654943.552      448308.312
     1654846.704      448436.148     1654795.638      448636.841
     1654787.353      448732.119     1654717.344      448821.183
     1654720.891      448865.611     1654694.353      448943.931
     1654681.408      449136.817     1654652.928       449304.46
     1654491.111      449639.098      1654486.58       449731.01
      1654519.59      449805.446     1654524.769      449882.471

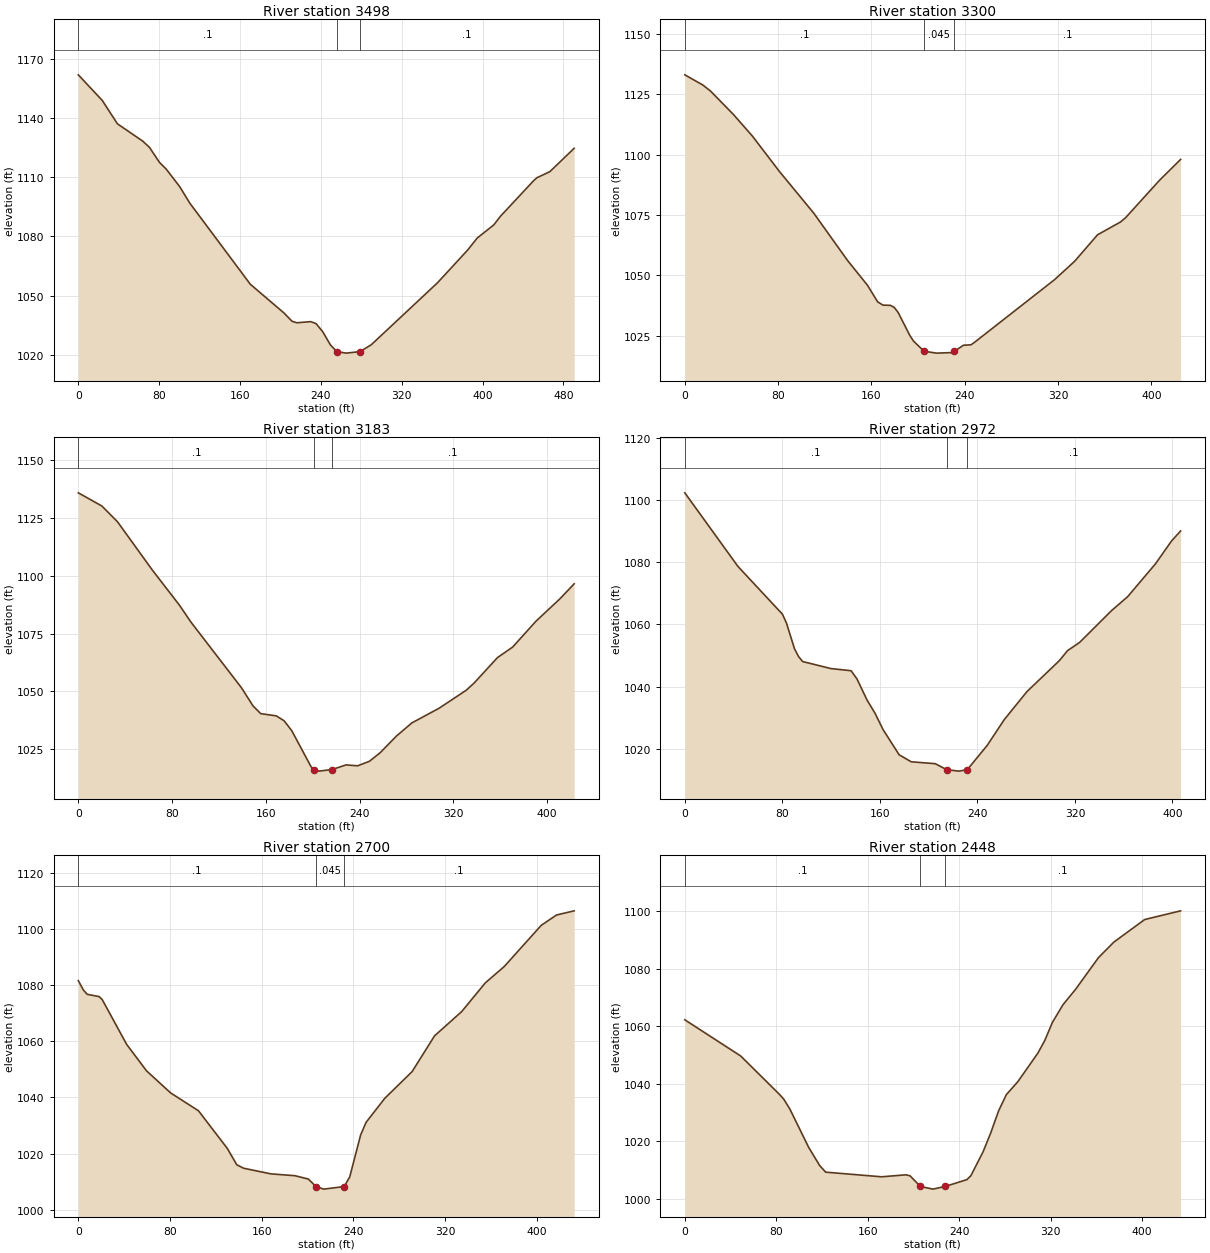
Type RM Length L Ch R = 1 ,3498    ,202.6,197.5,190.4
XS GIS Cut Line= 4
1655189.03368426446741.4804068511655393.36140086446776.239070083
1655468.69593277446824.2664459631655662.69043826446824.931837416
#Sta/Elev= 30
       0    1162    23.7 1148.99    38.7 1137.13    63.7 1128.36    70.3 1125.24
    80.3 1117.57      87 1114.13   100.3 1105.25   110.3 1096.88   170.2  1055.7
   203.4 1041.18   211.4 1036.95   216.2 1036.17     230 1036.74   235.2 1035.75
   241.7 1031.73   249.4 1024.97  255.761021.537     265 1020.76  278.741021.535
   289.8 1024.99   355.3 1056.42   385.4 1073.17   394.7 1079.18   411.1 1085.85
   417.6 1090.18   450.4 1108.23   453.7 1109.76   466.6 1112.88   490.6 1124.71
#Mann= 3 ,-1,0
       0      .1       0  255.76    .045       0  278.74      .1       0
Bank Sta=255.76,278.74
XS Rating Curve= 0 ,0
Exp/Cntr=0.3,0.1

Type RM Length L Ch R = 1 ,3300    ,117.4,116.7,113.8
XS GIS Cut Line= 6
1655180.74396834 446981.877331511655268.10107709446986.876009166
1655342.97855201446991.1604494151655442.81529459446996.873036429
1655517.69309759447001.1574766781655605.05020633447006.156154335
#Sta/Elev= 30
       0 1133.11    15.3 1128.94    21.9 1126.45    41.6 1116.72      58 1107.68
      81 1093.11   110.6 1075.72   139.5 1056.14   156.6 1045.86   165.3 1038.98
   169.8 1037.63   176.3 1037.52   179.6 1036.62   182.9 1034.56   192.8 1025.13
     196 1022.74  205.091018.485   215.8 1017.72   228.9 1017.94  231.121018.485
   238.8 1020.98   245.3 1021.18   248.3 1022.18   316.7 1048.09   334.1 1055.77
   353.8 1066.79   373.5  1072.1     378 1073.96   406.8 1089.33     425 1098.05
#Mann= 3 ,-1,0
       0      .1       0  205.09    .045       0  231.12      .1       0
Bank Sta=205.09,231.12
XS Rating Curve= 0 ,0
Exp/Cntr(USF)=0,0
Exp/Cntr=0.3,0.1

Type RM Length L Ch R = 1 ,3183    ,208.7,211.3,209.9
XS GIS Cut Line= 2
 1655192.4635886447136.1681333531655612.23193672447082.316272903
#Sta/Elev= 30
       0 1135.96    20.1 1130.25    33.4 1123.46    63.1 1102.59    86.3 1087.35
    96.2 1079.97   139.2 1051.64   149.1 1043.77   155.7 1040.41     169 1039.45
   175.6 1037.34   182.2 1033.02   198.7 1017.39  201.44 1016.24   205.4 1015.54
   216.6 1016.24   228.5 1018.23   238.4 1017.84   248.4 1019.78   257.7 1023.54
   271.5 1030.71   284.7 1036.41   307.9 1042.75     331 1050.51   337.7 1053.59
   357.7 1064.65   370.7 1069.22   390.6 1080.41   410.9 1090.03   423.2 1096.59
#Mann= 3 ,-1,0
       0      .1       0  201.44    .045       0   216.6      .1       0
Bank Sta=201.44,216.6
XS Rating Curve= 0 ,0
Exp/Cntr(USF)=0,0
Exp/Cntr=0.3,0.1

Type RM Length L Ch R = 1 ,2972    ,262.3,272.3,277.7
XS GIS Cut Line= 3
1655241.58242933447332.1682975891655357.81960302447313.871107562
1655646.24996203447295.896559878
#Sta/Elev= 30
       0 1102.25    43.6 1078.63    80.1  1063.3    83.4 1060.45      90  1052.2
    93.4 1049.66    96.7  1048.1   119.9 1045.85   136.4 1045.16   141.2 1042.55
   149.5 1035.75   156.1 1031.47   162.6 1026.29   175.8 1018.19   185.7 1015.94
   205.4 1015.33  214.88  1013.4   224.9 1012.94   231.7  1013.4   248.1 1021.23
     262 1029.45   280.6 1038.44   307.3 1048.42   313.9 1051.59   323.9 1054.26
     350 1064.44   363.2  1068.9   386.2 1079.53   399.3 1086.83   406.7 1090.01
#Mann= 3 ,-1,0
       0      .1       0  214.88    .045       0   231.7      .1       0
Bank Sta=214.88,231.7
XS Rating Curve= 0 ,0
Exp/Cntr(USF)=0,0
Exp/Cntr=0.3,0.1

Type RM Length L Ch R = 1 ,2700    ,253.6,251.5,249.1
XS GIS Cut Line= 6
1655231.34819785447472.2270725821655319.05307493447501.065925673
1655390.37970392 447532.591453181655473.91693842447587.563456088
1655536.32101309447629.1654070021655609.12565751447677.701071084
#Sta/Elev= 30
       0 1081.66     4.3 1078.39     7.7 1076.79    18.1 1075.98    20.8 1074.95
    42.2 1058.92    59.5 1049.52    80.5 1041.65   104.9 1035.25     130 1021.86
   138.3 1016.01   144.3 1014.77   168.1 1012.76     189 1012.11   200.8 1010.91
  207.381008.243   214.2 1007.32  232.081008.242   236.9 1011.67   246.4  1026.6
   251.1 1031.09   267.5 1039.71   291.4 1049.24   310.9 1061.96   334.6 1070.62
   355.2 1080.85   371.8 1086.71     404 1101.36   417.4 1105.07   432.8 1106.56
#Mann= 3 ,-1,0
       0      .1       0  207.38    .045       0  232.08      .1       0
Bank Sta=207.38,232.08
XS Rating Curve= 0 ,0
Exp/Cntr(USF)=0,0
Exp/Cntr=0.3,0.1

Type RM Length L Ch R = 1 ,2448    ,153,154.2,154
XS GIS Cut Line= 6
1655123.66039533447681.5884686771655200.27310299447723.858069172
1655265.94127874 447760.08929593 1655358.9023789447798.703063837
1655436.08299881447815.9763232531655525.20093082447835.881139091
#Sta/Elev= 30
       0 1062.23    48.9 1049.66    82.6 1036.41    86.4 1034.76    91.8 1031.31
   108.3 1017.96   117.9 1011.66   123.2 1009.33   172.1 1007.72   193.4 1008.41
     197 1008.05  206.041004.372     217 1003.44  227.751004.376   246.7 1006.74
   250.2 1008.11   260.9 1016.44   267.6 1023.02   274.4 1030.58   281.2 1036.25
   291.2 1040.72   308.8 1050.68   314.8 1055.04   321.5 1061.34   330.7 1067.44
   341.7 1072.79   361.8 1083.83   375.3 1089.23   402.2 1097.04   433.6 1100.06
#Mann= 3 ,-1,0
       0      .1       0  206.04    .045       0  227.75      .1       0
Bank Sta=206.04,227.75
XS Rating Curve= 0 ,0
Exp/Cntr(USF)=0,0
Exp/Cntr=0.3,0.1

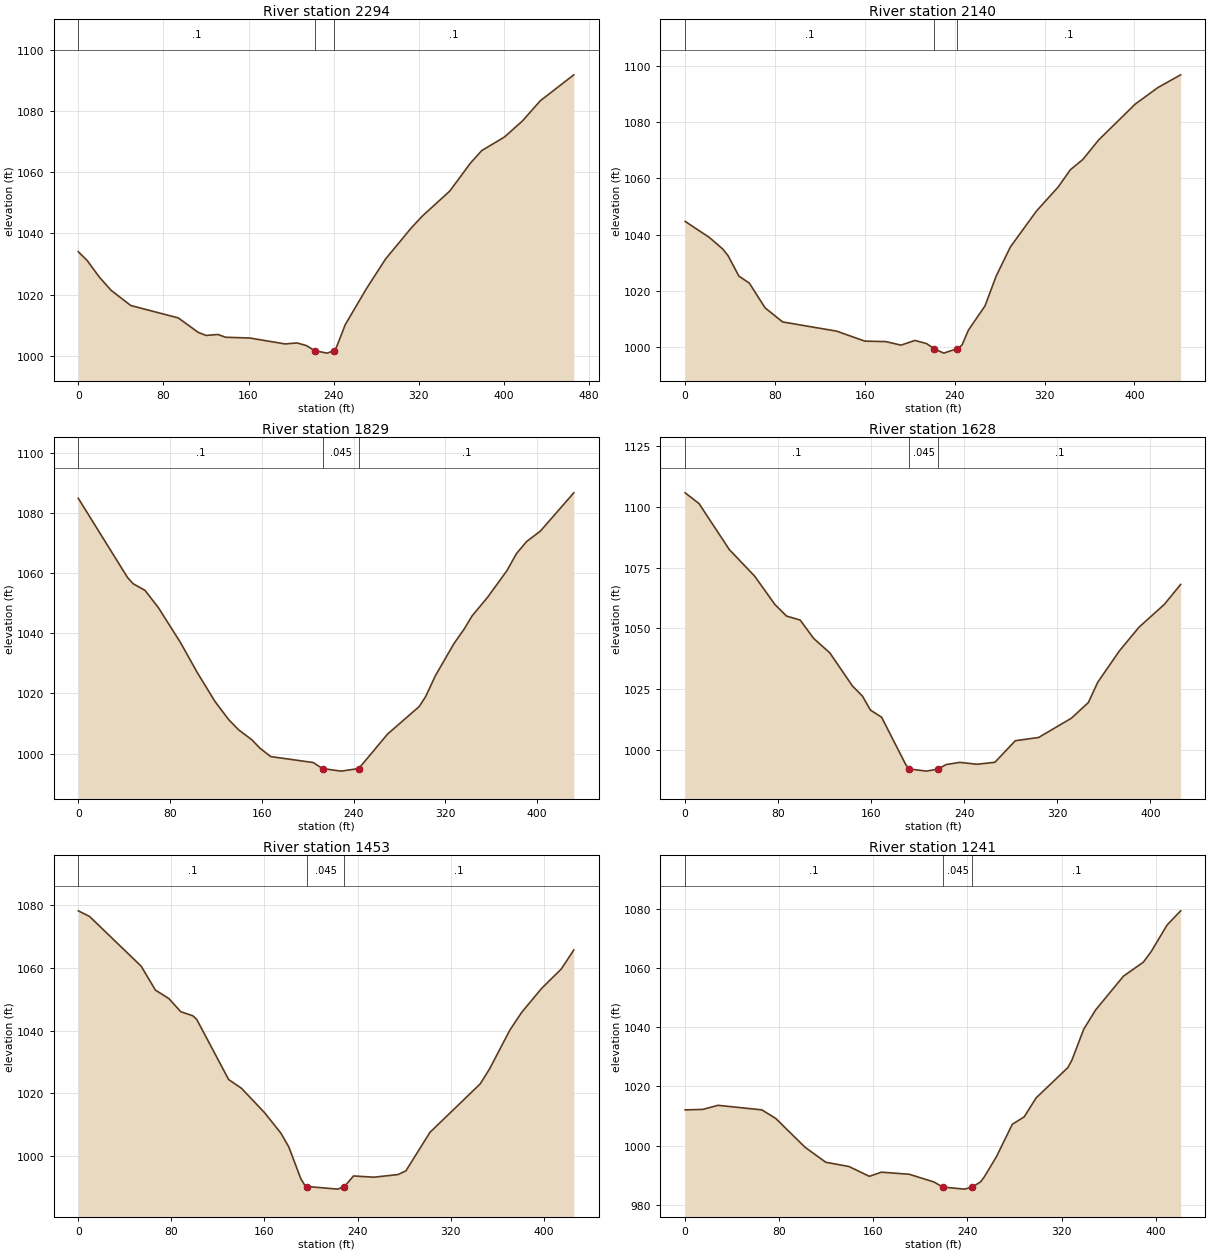
Type RM Length L Ch R = 1 ,2294    ,148.8,154.5,157.1
XS GIS Cut Line= 3
1655086.87514997447815.209546939 1655313.1355989447936.018293424
 1655510.7295656447867.423496691
#Sta/Elev= 30
       0 1034.05     8.4 1031.15    19.6 1025.82    30.8 1021.44    49.3 1016.47
      94 1012.41   112.6 1007.71     120 1006.69   131.2    1007   138.6 1006.09
   161.2 1005.85   194.4 1003.91   205.6 1004.24   214.5 1003.36  222.281001.698
   233.9 1000.91  240.381001.696   242.7 1002.86   250.9 1010.22   270.8 1021.97
   288.8 1031.67   313.1 1041.88   323.5 1045.74   349.1 1053.85   368.7 1063.05
   379.1 1067.06   400.6 1071.54   417.3 1076.72   434.1 1083.33   465.7 1091.84
#Mann= 3 ,-1,0
       0      .1       0  222.28    .045       0  240.38      .1       0
Bank Sta=222.28,240.38
XS Rating Curve= 0 ,0
Exp/Cntr(USF)=0,0
Exp/Cntr=0.3,0.1

Type RM Length L Ch R = 1 ,2140    ,304.2,310.6,311.8
XS GIS Cut Line= 2
1655057.34395267447861.2131712591655328.59295497448209.188216844
#Sta/Elev= 30
       0 1044.71    21.6 1038.99    33.5 1034.88    38.3 1032.46    47.8 1025.26
    57.2 1022.73    71.2 1013.93    86.8 1008.94   134.9 1005.66     160 1002.11
   178.7 1001.94   192.2 1000.68   204.6 1002.35   214.9 1001.25  221.65999.4345
   230.2  997.84  242.35999.4328   246.5  1000.7   252.3 1006.07     267 1014.64
   276.9 1025.22   289.6 1035.63   312.8 1048.39   332.3 1057.03     343 1063.09
   354.1 1066.74   368.1 1073.65   400.8 1086.47     421 1092.35   441.2 1096.87
#Mann= 3 ,-1,0
       0      .1       0  221.65    .045       0  242.35      .1       0
Bank Sta=221.65,242.35
XS Rating Curve= 0 ,0
Exp/Cntr(USF)=0,0
Exp/Cntr=0.3,0.1

Type RM Length L Ch R = 1 ,1829    ,204.8,201.3,197.4
XS GIS Cut Line= 6
1654870.69141308448078.9298398291654949.22964183448126.740111659
 1655008.0822144448175.1527444971655064.63295432448257.809731404
1655111.03213974448317.3840873191655165.32074507448386.792741159
#Sta/Elev= 30
       0  1084.8    42.9  1058.5    47.7 1056.45    58.2  1054.2    69.8 1048.48
      89 1036.93   103.6 1026.98   119.1 1017.33   131.1 1011.26   139.8 1007.86
   151.3 1004.57   158.3  1001.8   167.7  998.99   204.7  997.02  212.91995.0168
     229  994.16  244.45995.0179   269.6 1006.48   297.2 1015.64   302.9 1019.02
   311.2 1025.82   327.3 1036.46   336.1 1041.22   343.3 1045.76   356.9 1051.99
   373.6 1060.76   381.9 1066.42   390.7 1070.42   402.8 1073.93   431.9 1086.63
#Mann= 3 ,-1,0
       0      .1       0  212.91    .045       0  244.45      .1       0
Bank Sta=212.91,244.45
XS Rating Curve= 0 ,0
Exp/Cntr(USF)=0,0
Exp/Cntr=0.3,0.1

Type RM Length L Ch R = 1 ,1628    ,179,174.7,169.2
XS GIS Cut Line= 2
 1654740.8297575448226.778327336 1655062.3038795448506.276528948
#Sta/Elev= 30
       0 1105.76    11.9 1101.36      38 1082.42    59.8 1071.49    77.1 1059.89
    87.2  1055.1    98.9 1053.47   110.5 1045.91   124.4 1039.96   143.9 1026.33
   152.4 1022.24   159.3 1016.47   168.9 1013.53   189.6  994.13  192.46992.2604
   207.6  991.38   217.5  992.26   224.4  994.08   236.1  994.98     251  994.21
   266.3  995.01   283.9 1003.89   303.9 1005.21   332.1 1013.14   346.7 1019.59
   354.7 1027.89   373.3 1040.77   390.2 1050.53   411.9 1059.87     426 1068.11
#Mann= 3 ,-1,0
       0      .1       0  192.46    .045       0   217.5      .1       0
Bank Sta=192.46,217.5
XS Rating Curve= 0 ,0
Exp/Cntr(USF)=0,0
Exp/Cntr=0.3,0.1

Type RM Length L Ch R = 1 ,1453    ,214.2,212.1,210.3
XS GIS Cut Line= 6
1654622.49551427448455.062514658 1654706.8293351448479.396783585
1654778.92827227448501.0109135761654873.33162677 448534.20900991
 1654944.9194101448556.8408544161655029.25880835448580.570793832
#Sta/Elev= 30
       0 1078.29     9.6 1076.51      54 1060.62    66.3 1052.95    77.9 1050.24
    88.1 1046.05    98.4 1044.76   101.8 1043.58   129.2 1024.38   140.2  1021.6
   160.1 1013.79   174.1 1007.26   180.9 1002.85   191.3  992.63   194.7  990.58
  196.75990.2146     223  989.38  228.74990.2151   236.5  993.59   253.9  993.19
   274.7  994.03   281.5  995.21   302.2 1007.52   345.4 1023.01   353.7 1027.97
   370.7 1040.09   380.9 1045.79     398 1053.45     415 1059.69   425.8 1065.78
#Mann= 3 ,-1,0
       0      .1       0  196.75    .045       0  228.74      .1       0
Bank Sta=196.75,228.74
XS Rating Curve= 0 ,0
Exp/Cntr(USF)=0,0
Exp/Cntr=0.3,0.1

Type RM Length L Ch R = 1 ,1241    ,341,340.9,338.7
XS GIS Cut Line= 3
1654579.66938309448644.2486786691654658.58556739448693.769305309
1654977.57595795448770.356624445
#Sta/Elev= 30
       0 1012.07      15 1012.24    27.9 1013.62    65.2 1012.08    77.1 1009.15
     102   999.4   119.5  994.37   139.3  992.91   156.6   989.6   166.8     991
   190.4  990.31   211.6  987.67  218.96985.9575   237.6  985.27     244985.9583
   251.1  987.72   254.4  989.48   264.6  996.24   278.1  1007.2   288.2 1009.72
   298.4 1016.16   325.3 1026.37   328.7 1028.83   338.8 1039.35     349 1045.92
   372.6 1057.31   389.5 1062.04   396.2 1065.65   409.7 1074.62   421.2 1079.41
#Mann= 3 ,-1,0
       0      .1       0  218.96    .045       0     244      .1       0
Bank Sta=218.96,244
XS Rating Curve= 0 ,0
Exp/Cntr(USF)=0,0
Exp/Cntr=0.3,0.1

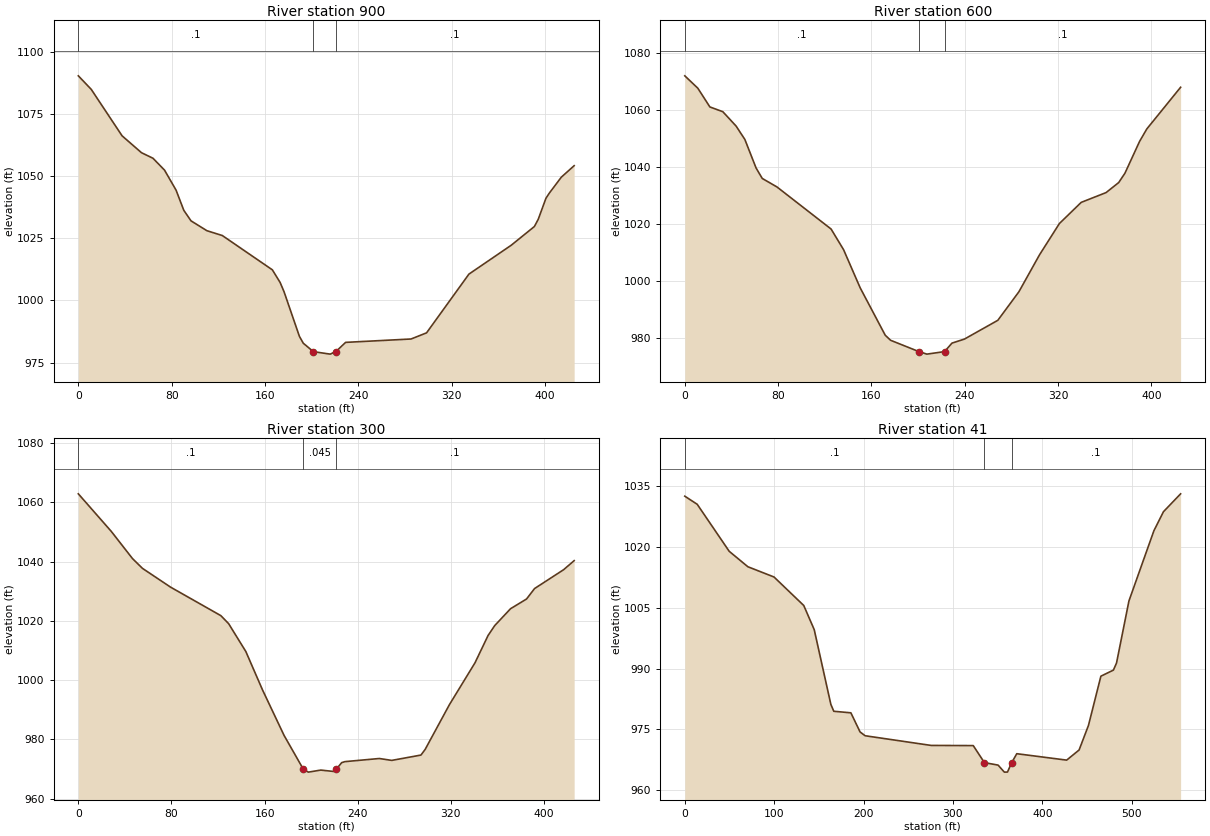
Type RM Length L Ch R = 1 ,900     ,296.5,300,302.9
XS GIS Cut Line= 6
1654479.59740476 449009.300442011654566.52078734 449019.32929334
1654641.02654384449027.926717088 1654740.3675525449039.388636425
1654814.87298092449047.985732093 1654901.7963635449058.016223833
#Sta/Elev= 30
       0 1090.44    11.1 1084.97    37.5 1066.29    54.1  1059.5      64 1057.25
    73.9 1052.47    83.8  1044.4    90.4 1036.31    96.6 1032.05   110.2 1028.09
   123.4 1026.15   166.3 1012.34     173 1007.23   176.3 1003.56   189.5  985.56
   192.8   982.8  201.48979.3967   215.9   978.4  220.69979.3959   229.1  983.13
   285.2  984.49   298.5  986.97   334.8 1010.61   371.1 1022.25   390.9 1029.77
   394.2 1032.67   400.8 1041.12   403.6 1043.15     414 1049.64     425 1054.26
#Mann= 3 ,-1,0
       0      .1       0  201.48    .045       0  220.69      .1       0
Bank Sta=201.48,220.69
XS Rating Curve= 0 ,0
Exp/Cntr(USF)=0,0
Exp/Cntr=0.3,0.1

Type RM Length L Ch R = 1 ,600     ,300.2,300,300
XS GIS Cut Line= 6
1654447.52463426449244.9203775821654528.04448634449279.170309082
1654596.97151384449308.7361948341654688.75643526449348.429356918
1654757.59520835449378.1989824181654837.90705559449412.929556012
#Sta/Elev= 30
       0 1071.87    11.2 1067.51    21.5 1060.95    32.6 1059.28      44 1054.23
    51.5 1049.53    61.1 1039.53    66.4 1035.86      79 1032.88   125.4 1018.11
   136.1 1010.87   150.3  997.51   171.8  980.86   176.4  979.08  200.71975.1016
   207.5  974.22  222.64975.1018     229  978.08   239.7   979.5   268.3  986.08
   286.4  996.11     304 1009.03   321.1 1020.05   339.8 1027.47   361.1  1030.9
   371.9 1034.41   377.3 1037.72   389.8 1048.84     396 1053.22     425 1067.86
#Mann= 3 ,-1,0
       0      .1       0  200.71    .045       0  222.64      .1       0
Bank Sta=200.71,222.64
XS Rating Curve= 0 ,0
Exp/Cntr(USF)=0,0
Exp/Cntr=0.3,0.1

Type RM Length L Ch R = 1 ,300     ,262.1,259.3,261
XS GIS Cut Line= 6
1654320.81196117449509.9310024231654399.68188217449547.959797755
1654468.39434317   449578.0197771654560.01030168449618.101389751
 1654628.7221065449648.1623532621654713.76097843 449672.04419525
#Sta/Elev= 30
       0 1062.89    28.3 1050.21    46.5 1041.04    55.1 1037.72    79.3 1031.37
   122.4 1021.77   129.1 1019.06   143.9 1009.64   158.2   996.7   176.7  981.35
  193.39 969.826   197.6  968.93   208.3  969.62   219.1  969.16  221.41969.8253
   226.2  972.13     229  972.47   258.5  973.53   269.2  972.89   294.3  974.69
   297.9  976.59   318.7  991.67   340.7 1005.82     352 1015.09   357.7 1018.42
   371.3 1024.11     385 1027.38   391.9 1030.91   416.8 1037.26   425.9 1040.33
#Mann= 3 ,-1,0
       0      .1       0  193.39    .045       0  221.41      .1       0
Bank Sta=193.39,221.41
XS Rating Curve= 0 ,0
Exp/Cntr(USF)=0,0
Exp/Cntr=0.3,0.1

Type RM Length L Ch R = 1 ,41      ,,,
XS GIS Cut Line= 4
1654300.07429354449581.3844419891654499.10158436449833.485677026
1654564.61473425449856.7055276211654718.86088464449801.143742268
#Sta/Elev= 30
       0  1032.5    13.9  1030.5    49.7 1018.91    70.6  1015.1    99.8 1012.58
   133.1 1005.55   144.8   999.6   163.4  981.18   166.7  979.48   185.8   979.1
   196.1  974.38   201.7  973.45   275.6  971.06   322.7  971.02   335.2  966.82
   350.5  966.21   357.5  964.48     361   964.5  365.59 966.758   371.4  969.02
   427.2  967.44   441.1  969.93   451.6  975.99   465.5  988.13   479.5  989.63
     483  991.38   496.9 1006.69   524.8 1023.98   535.5 1028.67   554.7 1033.08
#Mann= 3 ,-1,0
       0      .1       0   335.2    .045       0  365.59      .1       0
Bank Sta=335.2,365.59
XS Rating Curve= 0 ,0
Exp/Cntr(USF)=0,0
Exp/Cntr=0.3,0.1
LCMann Table=0

Chan Stop Cuts=-1
Use User Specified Reach Order=0
Composite Channel Slope=5